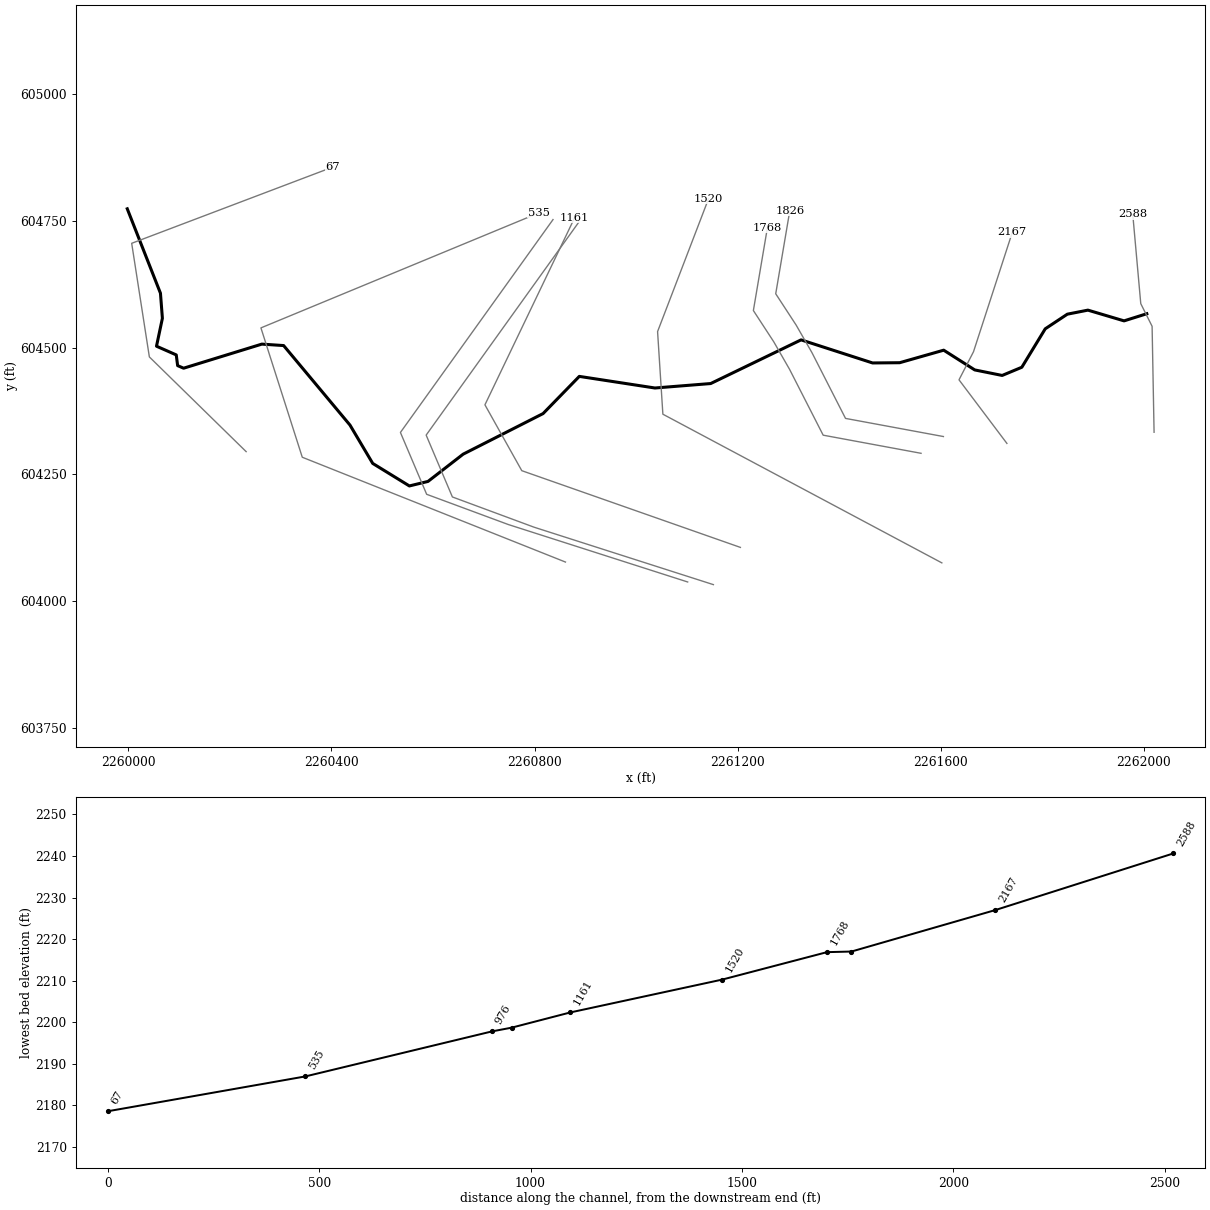
--- DRYRN2.prj (project) ---

Proj Title=DRYRN2
Current Plan=p01
Default Exp/Contr=0,0
English Units
Geom File=g01
Flow File=f01
Plan File=p01
BEGIN DESCRIPTION:
----------MODEL BY WOOD PLC 2022----------
AFH study
Randolph County, WV
HEC-RAS Version: RAS 6.2
Vertical Datum: NAVD88
Projection: NAD 1983 StatePlane West Virginia S FIPS 4702 (US Feet)
Terrain: 1-meter LIDAR (FEMA Region III 3DEP collected 2016-2018)
Land Use: 2019 NLCD
Hydrologic Method:
WV SIR2010-5033 regression equations
Additional Model Notes:
None
END DESCRIPTION:
DSS Export Rating Curves= 0
DSS Export Rating Curve Sorted= 0
DSS Export Volume Flow Curves= 0
DXF OffsetX= 0
DXF OffsetY= 0
DXF ScaleX= 0
DXF ScaleY= 0

--- DRYRN2.p01 (plan) ---

Plan Title=Floodplain
Program Version=6.20
Short Identifier=Floodplain
Geom File=g01
Flow File=f01
Subcritical Flow
K Sum by GR= 0
Std Step Tol= 0.01
Critical Tol= 0.01
Num of Std Step Trials= 20
Max Error Tol= 0.3
Flow Tol Ratio= 0.001
Split Flow NTrial= 30
Split Flow Tol= 0.02
Split Flow Ratio= 0.02
Log Output Level= 0
Friction Slope Method= 1
Unsteady Friction Slope Method= 2
Unsteady Bridges Friction Slope Method= 1
Parabolic Critical Depth
Global Vel Dist= 0 , 0 , 0
Global Log Level= 0
CheckData=True
Encroach Param=-1 ,0,0, 0
Mapping Interval=1HOUR
Computation Time Step Use Courant=        0
Computation Time Step Use Time Series=    0
Computation Time Step Count To Double=0
Computation Time Step Max Doubling=0
Computation Time Step Max Halving=0
Computation Time Step Residence Courant=0
Run HTab= 0
Run UNet= 0
Run Sediment= 0
Run PostProcess= 0
Run WQNet= 0
Run RASMapper=-1
UNET Theta= 0
UNET Theta Warmup= 0
UNET ZTol= 0
UNET ZSATol= 0
UNET MxIter= 0
UNET Max Iter WO Improvement= 0
UNET MaxInSteps= 0
UNET DtIC= 0
UNET DtMin= 0
UNET MaxCRTS= 0
UNET WFStab= 0
UNET SFStab= 0
UNET WFX= 1
UNET SFX= 1
UNET Gravity=32.174
UNET 1D Methodology=Finite Difference
UNET DSS MLevel= 1
UNET Pardiso=0
UNET DZMax Abort= 0
UNET Use Existing IB Tables= 0
UNET Froude Reduction=False
UNET Froude Limit= 0
UNET Froude Power= 0
UNET D1 Cores= 0
UNET WindReference=Eulerian
UNET WindDragFormulation=Hsu (1988)
UNET D2 Coriolis=0
UNET D2 Cores= 0
UNET D2 Theta= 1
UNET D2 Theta Warmup= 1
UNET D2 Z Tol= 0.01
UNET D2 Volume Tol= 0.01
UNET D2 Max Iterations= 20
UNET D2 Equation= 0
UNET D2 RampUpFraction=0.1
UNET D2 TimeSlices= 1
UNET D2 Turbulence Formulation=Non-Conservative (original)
UNET D2 Eddy Viscosity=0.3
UNET D2 Transverse Eddy Viscosity=0.1
UNET D2 Smagorinsky Mixing=0
UNET D2 BCVolumeCheck=0
UNET D2 Cores=0
UNET D2 SolverType=PARDISO (Direct)
UNET D2 Minimum Iterations= 2147483647
UNET D2 Maximum Iterations= 2147483647
UNET D2 Restart Number= 10
UNET D2 Relaxation Coeff=1.3
UNET D2 SOR Precondition Iterations= 10
UNET D2 ILUT Maximum Fill= 8
UNET D2 ILUT Tolerance=1E-08
UNET D1D2 MaxIter= 0
UNET D1D2 ZTol=0.01
UNET D1D2 QTol=0.1
UNET D1D2 MinQTol=1
Write IC File= 0
Write IC File at Fixed DateTime=0
Write IC File at Sim End=0
Echo Input=False
Echo Parameters=False
Echo Output=False
Write Detailed= 0
HDF Write Warmup=0
HDF Write Time Slices=0
HDF Flush=0
HDF Compression= 1
HDF Chunk Size= 1
HDF Spatial Parts= 1
HDF Use Max Rows=0
HDF Fixed Rows= 1
Calibration Method= 0
Calibration Iterations= 20
Calibration Max Change=0.05
Calibration Tolerance=0.2
Calibration Maximum=1.5
Calibration Minimum=0.5
Calibration Optimization Method= 1
WQ AD Non Conservative
WQ ULTIMATE=-1
WQ Max Comp Step=1HOUR
WQ Output Interval=15MIN
WQ Output Selected Increments= 0
WQ Output face flow=0
WQ Output face velocity=0
WQ Output face area=0
WQ Output face dispersion=0
WQ Output cell volume=0
WQ Output cell surface area=0
WQ Output cell continuity=0
WQ Output cumulative cell continuity=0
WQ Output face conc=0
WQ Output face dconc_dx=0
WQ Output face courant=0
WQ Output face peclet=0
WQ Output face adv mass=0
WQ Output face disp mass=0
WQ Output cell mass=0
WQ Output cell source sink temp=0
WQ Output nsm pathways=0
WQ Output nsm derived pathways=0
WQ Create Restart=0
WQ Fixed Restart=0
WQ System Summary=0
WQ Write To DSS=0
Sorting and Armoring Iterations= 10
XS Update Threshold= 0.02
Bed Roughness Predictor= 0
Hydraulics Update Threshold= 0.02
Energy Slope Method= 1
Volume Change Method= 1
Sediment Retention Method= 0
Sediment TS Multiplier= 1
Warm Up Method= 0
XS Weighting Method= 0
Number of US Weighted Cross Sections= 1
Number of DS Weighted Cross Sections= 1
Upstream XS Weight=0
Main XS Weight=1
Downstream XS Weight=0
Number of DS XS's Weighted with US Boundary= 1
Upstream Boundary Weight= 1
Weight of XSs Associated with US Boundary= 0
Number of US XS's Weighted with DS Boundary= 1
Downstream Boundary Weight= 0.5
Weight of XSs Associated with DS Boundary= 0.5
Percentile Method= 0
Sediment Output Level= 3
Mass or Volume Output= 0
Output Increment Type= 1
Profile and TS Output Increment= 1
Transport Output Increment 1
XS Output Flag= 0
XS Output Increment= 10
Read HDF5 Sediment Hotstart= 0
Sediment Hotstart Type= 0
Write Gradation File= 0
Read Gradation Hotstart= 0
Write HDF5 File= 1
Write Binary Output= 1
Write DSS Sediment File= 0
DSS Sediment Output Type= 1
SV Curve= 0
Specific Gage Flag= 0
Subcell Erosion Methods= 0
Subcell Deposition Methods= 0
Advection Scheme= 1
Matrix Solver= 0
Implicit Weighting Factor= 1
Maximum Outer Loop Convergence Iterations= 5
Convergence Maximum Absolute= 0.001
Convergence RMSE= 0.0001
Grain Fractions Max Abs Error= 0.001
Max Subgrid Regions= 1
Max Subgrid Length Scale= 3.402823E+38
Initial Layer Thickness= 3.402823E+38
Min Layer Thickness= 3.402823E+38
Max Layer Thickness= 3.402823E+38
Number of Layers= 5

--- DRYRN2.f01 (steady flow) ---

Flow Title=Flow
Program Version=6.20
Number of Profiles= 1
Profile Names=P100yr
River Rch & RM=DRYRN2,Main,2588
     306
Boundary for River Rch & Prof#=DRYRN2,Main            , 1
Up Type= 0
Dn Type= 3
Dn Slope=0.01891
DSS Import GetInterval= 0
DSS Import GetPeak= 0
DSS Import FillOption= 0

--- DRYRN2.g01 (geometry) ---

Geom Title=Geometry
Program Version=6.20

River Reach=DRYRN2          ,Main
Reach XY= 30
2262005.80800001604566.5950000142261961.01700003604552.533000007
2261889.82500002604573.6770000162261849.31399998 604565.71100001
2261805.80800003604536.9080000222261759.68600003604461.192000002
2261720.98000002604445.0460000192261666.96000002604455.925000012
2261605.83100003604494.8070000112261519.10700002      604470.125
2261465.71800001604469.6610000132261324.94200003604515.121000022
2261146.95399998604429.0949999992261037.14399999604420.323000014
2260888.17200004604443.1940000062260816.81100002      604369.934
2260659.45399998604290.0330000222260590.20399998604236.328999996
2260553.51900002      604227.4342260481.32900003604271.804000005
2260436.53700002604347.3250000182260305.89400002 604503.90200001
2260262.95900002604506.7539999932260108.90485844604459.321022496
 2260097.1437721604464.384507209 2260094.4268472604485.498350561
2260055.51233417604502.6426125762260067.12400003604557.610000014
2260063.30600001604607.013999999     2259997.929      604773.244

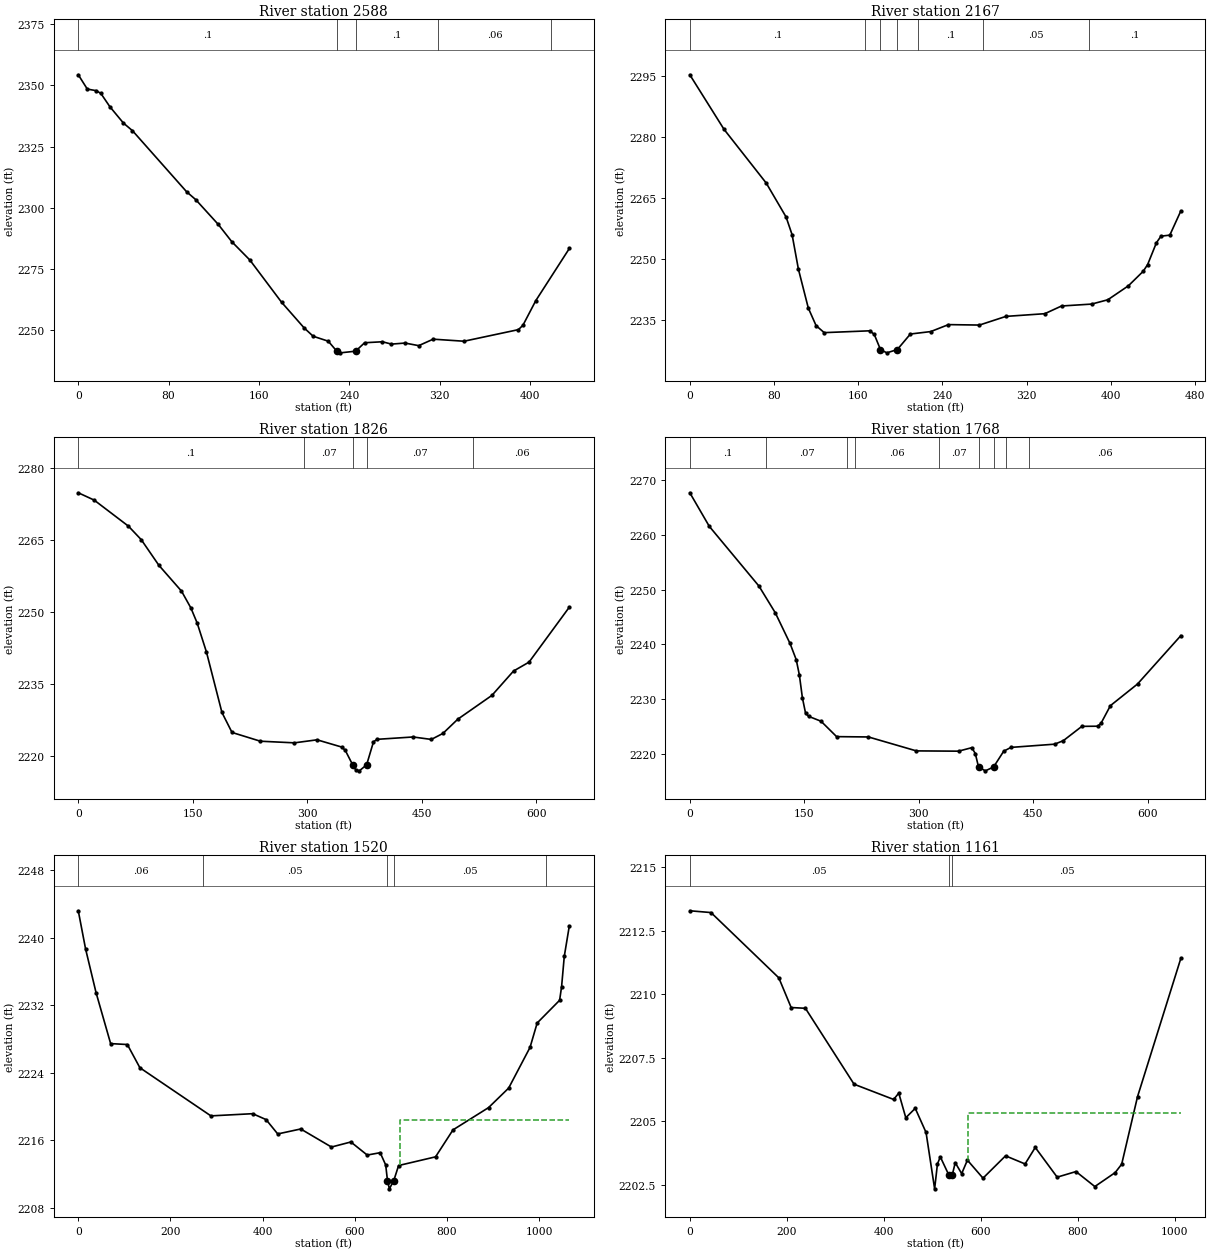
Type RM Length L Ch R = 1 ,2588    ,427.3,421.3,411.8
XS GIS Cut Line= 4
2262020.13456371604333.1770322352262016.25117189604541.819233547
2261993.93768772604586.4462018872261978.17945359604762.069678611
#Sta/Elev= 30
       0 2354.37       8 2348.52      16 2347.86      20 2346.74      28 2341.29
      40 2334.61      48  2331.5      96 2306.49     104  2303.3     124 2293.15
     136 2286.07     152 2278.57     180 2261.35     200 2250.84     208 2247.42
   221.4 2245.39  228.952241.309   232.1 2240.63  245.612241.307   253.6 2244.76
   269.3 2245.16   277.4  2244.2   289.4 2244.63   301.5 2243.57   314.3 2246.22
   341.6 2245.38   389.8 2250.12   393.8  2251.9   405.2 2261.99   434.9 2283.31
#Mann= 5 ,-1,0
       0      .1       0  228.95    .045       0  245.61      .1       0
  318.57     .06       0  418.57      .1       0
Bank Sta=228.95,245.61
XS Rating Curve= 0 ,0
Exp/Cntr(USF)=0,0
Exp/Cntr=0.3,0.1

Type RM Length L Ch R = 1 ,2167    ,331.6,340.4,348.7
XS GIS Cut Line= 4
2261730.28562631604311.2070769582261635.96410383604436.440820243
2261664.52536357604491.778260983 2261741.0506558604727.214521716
#Sta/Elev= 30
       0 2295.26    32.5 2281.87    72.6 2268.68    91.5 2260.33    97.2 2255.99
   103.2 2247.52   112.6 2237.98     120 2233.67   127.7 2231.95   171.1  2232.4
   175.3  2231.5  181.162227.795   187.2 2226.99  197.152227.795   209.6 2231.61
   228.9 2232.21   245.8 2233.92   275.2 2233.81   300.4 2235.94   337.3  2236.6
   353.2 2238.49   381.8 2238.96   397.2 2240.02   416.7 2243.44   430.8 2247.01
     435 2248.65   443.4 2254.03   447.7 2255.63   456.1 2255.89   466.6 2261.84
#Mann= 7 ,-1,0
       0      .1       0  166.78     .05       0  181.16    .045       0
  197.15     .05       0  216.78      .1       0  279.05     .05       0
  379.05      .1       0
Bank Sta=181.16,197.15
XS Rating Curve= 0 ,0
Exp/Cntr(USF)=0,0
Exp/Cntr=0.3,0.1

Type RM Length L Ch R = 1 ,1826    ,57.9,58.1,57
XS GIS Cut Line= 6
2261605.25409737604324.7395859262261412.46559414604360.441160597
  2261346.417681604489.8593687812261315.17880316604544.304270155
2261275.01453166604605.8894864632261302.68325203604769.224190584
#Sta/Elev= 30
       0 2274.81    20.8 2273.29    65.7 2267.87    82.5 2265.06   105.6 2259.73
   135.2 2254.37   147.5 2250.87   155.8 2247.71   167.9 2241.71   188.2 2229.13
   201.4 2224.98   238.5 2223.16   283.1 2222.82   312.8 2223.45   345.2 2221.94
   349.8 2221.25  359.432218.258   363.6 2217.19   368.2    2217  377.752218.255
   386.7 2223.02   391.3 2223.55   438.6 2224.04   462.5 2223.53   477.7 2224.78
   497.2 2227.74   541.9 2232.69   570.2 2237.75   590.5  2239.6   643.3 2251.03
#Mann= 5 ,-1,0
       0      .1       0  296.07     .07       0  359.43    .045       0
  377.75     .07       0  517.66     .06       0
Bank Sta=359.43,377.75
XS Rating Curve= 0 ,0
Exp/Cntr(USF)=0,0
Exp/Cntr=0.3,0.1

Type RM Length L Ch R = 1 ,1768    ,250.9,247.9,243.3
XS GIS Cut Line= 6
2261561.23904509604291.7156293552261368.45054187604327.417204026
2261302.40262873 604456.835412212261271.16375089604511.280313584
2261230.99947938604572.8655298922261258.66819975604736.200234013
#Sta/Elev= 30
       0 2267.74    25.5  2261.6    90.6 2250.66     112 2245.77   131.3 2240.16
   139.4  2237.2   143.5 2234.42   147.5 2230.21   151.6 2227.43   155.7 2226.82
   171.9 2225.93   192.3 2223.11     234 2223.05   296.8  2220.5     352 2220.45
   369.4 2221.09     374 2220.02  378.232217.559   387.2 2216.85  397.952217.556
   411.2 2220.44   420.7 2221.14     478 2221.73   489.4 2222.38   513.6 2224.99
   534.5 2225.02   538.8 2225.58     551 2228.78   586.5 2232.74   643.3  2241.6
#Mann= 9 ,-1,0
       0      .1       0     100     .07       0  206.07     .05       0
  216.07     .06       0  326.07     .07       0  378.23    .045       0
  397.95     .07       0  414.13     .05       0  444.13     .06       0
Bank Sta=378.23,397.95
XS Rating Curve= 0 ,0
Exp/Cntr(USF)=0,0
Exp/Cntr=0.3,0.1

Type RM Length L Ch R = 1 ,1520    ,357.3,359.3,362.2
XS GIS Cut Line= 4
2261602.16042503604075.9271563112261052.76795496604368.728712771
 2261042.3358884604531.4334952492261142.63204829604792.817864097
#Sta/Elev= 30
       0 2243.17    15.8 2238.66    38.5 2233.49    70.2 2227.44   106.5 2227.33
   133.7 2224.58   287.8 2218.88   378.5 2219.14   407.5 2218.44   432.8 2216.74
   482.7 2217.33   549.4 2215.19   591.5 2215.79     627 2214.24   655.1 2214.52
   667.1 2213.07  670.962211.216   675.1 2210.24   684.62211.214   695.1    2213
   775.3 2214.03   813.1 2217.22   890.3 2219.86   933.9 2222.17   980.3 2226.99
   995.8 2229.88  1044.5 2232.57  1048.8 2234.18  1054.6 2237.76  1065.6 2241.39
#Mann= 5 ,-1,0
       0     .06       0     270     .05       0  670.96    .045       0
   684.6     .05       0 1015.59     .06       0
#XS Ineff= 2 , 0
                          698.34         2218.45
Permanent Ineff=
       F       F
Bank Sta=670.96,684.6
XS Rating Curve= 0 ,0
Exp/Cntr(USF)=0,0
Exp/Cntr=0.3,0.1

Type RM Length L Ch R = 1 ,1161    ,139.9,139,138
XS GIS Cut Line= 4
2261205.43133736604106.4138210712260774.89724916604257.505003081
2260702.33573049604387.1993535862260878.81633749 604755.30422273
#Sta/Elev= 30
       0 2213.28    43.7 2213.21   183.6 2210.64   209.1 2209.47   238.5 2209.44
   338.9 2206.45   420.5 2205.85   431.1  2206.1   445.6 2205.13   465.1  2205.5
   487.4 2204.55   505.1 2202.33   510.9 2203.31   516.8 2203.59   534.5 2202.87
  541.412202.871   547.6 2203.36   560.9 2202.93   572.7 2203.46   604.9 2202.75
   651.4 2203.63   691.7 2203.31   712.7 2203.96   757.9 2202.79   796.7 2203.01
   835.6 2202.42   877.6 2202.97     891  2203.3   923.7 2205.96  1013.1 2211.41
#Mann= 3 ,-1,0
       0     .05       0   534.5    .045       0  541.41     .05       0
#XS Ineff= 2 , 0
                          573.57         2205.31
Permanent Ineff=
       F       F
Bank Sta=534.5,541.41
XS Rating Curve= 0 ,0
Exp/Cntr(USF)=0,0
Exp/Cntr=0.3,0.1

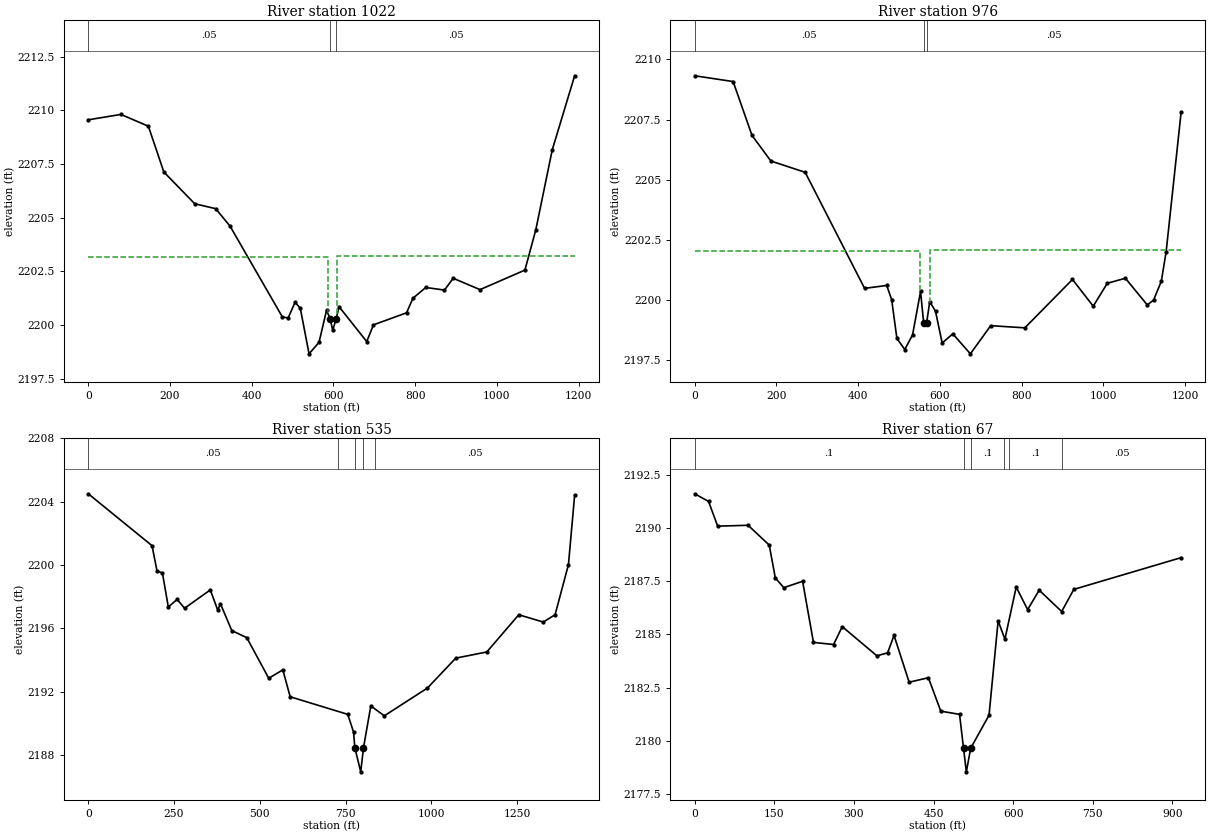
Type RM Length L Ch R = 1 ,1022    ,45.3,46.1,47.3
XS GIS Cut Line= 5
 2261152.2629228604033.0807925812260799.00884022 604146.21555392
2260638.24096813604205.7496662422260586.56661996604327.554911936
 2260887.0915289604746.796218181
#Sta/Elev= 30
       0 2209.56    79.9 2209.81   147.1 2209.26   184.9 2207.13   260.5 2205.65
   311.9 2205.42   346.9 2204.61     475 2200.38   489.1 2200.33   506.2 2201.06
     519 2200.78   540.4 2198.66   564.9  2199.2   583.2 2200.69  591.82  2200.3
   598.4 2199.76   606.9  2200.3   613.7 2200.86   681.6 2199.23     698 2200.01
     779 2200.57   794.8 2201.25   826.1 2201.75   871.9 2201.63   893.2 2202.18
   958.9 2201.65  1068.8 2202.56  1095.5 2204.44  1135.7 2208.16  1190.5 2211.61
#Mann= 3 ,-1,0
       0     .05       0  591.82    .045       0   606.9     .05       0
#XS Ineff= 2 , 0
          585.87 2203.18  609.67         2203.21
Permanent Ineff=
       F       F
Bank Sta=591.82,606.9
XS Rating Curve= 0 ,0
Exp/Cntr(USF)=0,0
Exp/Cntr=0.3,0.1

Type RM Length L Ch R = 1 ,976     ,426.9,441.4,447.4
XS GIS Cut Line= 5
2261101.59302082604038.3133178532260748.33893824604151.448079192
2260587.57106615604210.9821915142260535.89671798604332.787437208
2260836.42162692604752.028743453
#Sta/Elev= 30
       0 2209.32    93.9 2209.08   140.2 2206.84   186.3 2205.78   270.3 2205.31
   415.7 2200.49   469.9 2200.61     482 2200.02   494.8 2198.41   514.1 2197.95
   533.2 2198.56   552.7 2200.36  560.412199.049   567.42199.036   575.2 2199.94
   589.3 2199.54   605.6 2198.22   631.7  2198.6   674.7 2197.77   724.4 2198.94
     808 2198.85   924.6 2200.86   975.4 2199.75  1009.8  2200.7  1054.1 2200.91
  1107.7  2199.8    1123    2200    1142 2200.78  1153.9 2202.01  1190.5  2207.8
#Mann= 3 ,-1,0
       0     .05       0  560.41    .045       0   567.4     .05       0
#XS Ineff= 2 , 0
          551.91 2202.06  576.95          2202.1
Permanent Ineff=
       F       F
Bank Sta=560.41,567.4
XS Rating Curve= 0 ,0
Exp/Cntr(USF)=0,0
Exp/Cntr=0.3,0.1

Type RM Length L Ch R = 1 ,535     ,480,467.5,448.7
XS GIS Cut Line= 4
2260860.92205124 604077.560326352260342.61091797604283.956021745
2260261.19621829604538.7160957692260808.85136063604765.308907989
#Sta/Elev= 30
       0 2204.49   185.9 2201.21   200.4 2199.61   216.1 2199.49   233.3 2197.34
   259.1 2197.82   280.7 2197.26   355.8 2198.42   377.4 2197.14   385.2 2197.55
   418.4 2195.85   462.2  2195.4   526.1 2192.84   567.2 2193.37   588.6 2191.67
   756.5 2190.56   773.3 2189.45   777.2 2188.45   794.3 2186.93   802.4 2188.45
   823.7 2191.09   863.2 2190.47   988.7 2192.22  1071.4 2194.11  1161.9  2194.5
  1255.1 2196.85  1326.4 2196.39    1361 2196.85    1400 2200.02    1418  2204.4
#Mann= 5 ,-1,0
       0     .05       0  727.89      .1       0   777.2    .045       0
   802.4      .1       0  835.35     .05       0
Bank Sta=777.2,802.4
XS Rating Curve= 0 ,0
Exp/Cntr(USF)=0,0
Exp/Cntr=0.3,0.1

Type RM Length L Ch R = 1 ,67      ,,,
XS GIS Cut Line= 4
2260232.06462343604294.9944367592260041.45514371  604481.5412511
 2260006.6487181604705.2913975922260402.65789713604855.408453996
#Sta/Elev= 30
       0  2191.6      26 2191.24    43.2 2190.08   100.5 2190.12   140.4 2189.19
   151.8 2187.65   167.8 2187.19   203.3 2187.49   223.7 2184.62   261.7 2184.52
     278 2185.36   343.3 2183.99   363.5 2184.13   375.6 2184.95   404.1 2182.75
   440.4 2182.96   463.7 2181.39   499.1 2181.24  506.592179.649   511.9 2178.54
  520.082179.649   554.7  2181.2   571.8 2185.63   584.6 2184.77   605.9 2187.22
   627.4 2186.16   649.3 2187.07   691.6 2186.07   714.5 2187.11   916.7  2188.6
#Mann= 6 ,-1,0
       0      .1       0  506.59    .045       0  520.08      .1       0
  583.15     .05       0  593.15      .1       0  693.15     .05       0
Bank Sta=506.59,520.08
XS Rating Curve= 0 ,0
Exp/Cntr(USF)=0,0
Exp/Cntr=0.3,0.1
LCMann Table=0

Chan Stop Cuts=-1
Use User Specified Reach Order=0
Composite Channel Slope=5